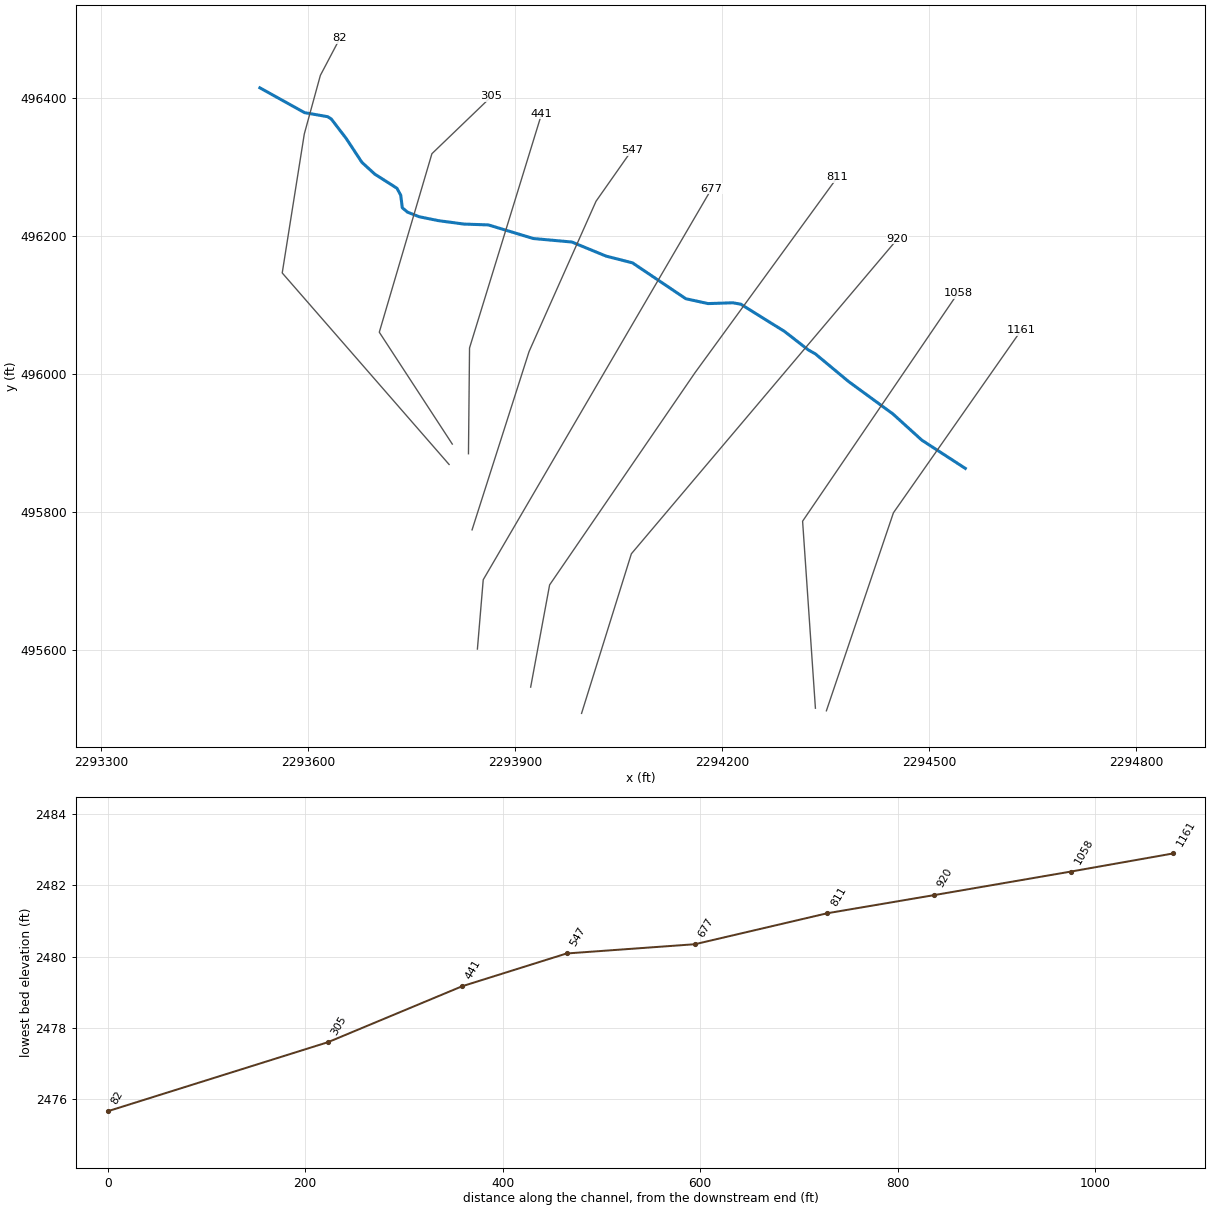
--- GUMBR.prj (project) ---

Proj Title=GUMBR
Current Plan=p01
Default Exp/Contr=0,0
English Units
Geom File=g01
Flow File=f01
Plan File=p01
Background Map Layer=Inundation Boundary (0_2pct Value_0)
Background Map Layer=Inundation Boundary (01pct Value_0)
BEGIN DESCRIPTION:
 ----------MODEL BY WOOD PLC 2021----------
Stream Name: Gum Branch
Flood Zone: Approximate
Pocahontas County, WV
HEC-RAS Version: RAS 6.0
Vertical Datum: NAVD88
Projection: NAD 1983 StatePlane West Virginia S FIPS 4702 (US Feet)
Terrain: 1-meter LIDAR (FEMA Region III 3DEP collected 2016-2018)
Land Use: 2019 NLCD
Hydrologic Method:
WV SIR2010-5033 regression equations
Model Notes:
END DESCRIPTION:
DSS Export Rating Curves= 0
DSS Export Rating Curve Sorted= 0
DSS Export Volume Flow Curves= 0
DXF OffsetX= 0
DXF OffsetY= 0
DXF ScaleX= 0
DXF ScaleY= 0

--- GUMBR.p01 (plan) ---

Plan Title=Floodplain
Program Version=6.00
Short Identifier=Floodplain
Geom File=g01
Flow File=f01
Subcritical Flow
K Sum by GR= 0
Std Step Tol= 0.01
Critical Tol= 0.01
Num of Std Step Trials= 20
Max Error Tol= 0.3
Flow Tol Ratio= 0.001
Split Flow NTrial= 30
Split Flow Tol= 0.02
Split Flow Ratio= 0.02
Log Output Level= 0
Friction Slope Method= 1
Unsteady Friction Slope Method= 2
Unsteady Bridges Friction Slope Method= 1
Parabolic Critical Depth
Global Vel Dist= 0 , 0 , 0
Global Log Level= 0
CheckData=True
Encroach Param=-1 ,0,0, 0
Mapping Interval=1HOUR
Computation Time Step Use Courant=        0
Computation Time Step Use Time Series=    0
Computation Time Step Count To Double=0
Computation Time Step Max Doubling=0
Computation Time Step Max Halving=0
Computation Time Step Residence Courant=0
Run HTab= 0
Run UNet= 0
Run Sediment= 0
Run PostProcess= 0
Run WQNet= 0
Run RASMapper=-1
UNET Theta= 0
UNET Theta Warmup= 0
UNET ZTol= 0
UNET ZSATol= 0
UNET MxIter= 0
UNET Max Iter WO Improvement= 0
UNET MaxInSteps= 0
UNET DtIC= 0
UNET DtMin= 0
UNET MaxCRTS= 0
UNET WFStab= 0
UNET SFStab= 0
UNET WFX= 1
UNET SFX= 1
UNET Gravity=32.174
UNET 1D Methodology=Finite Difference
UNET DSS MLevel= 1
UNET Pardiso=0
UNET DZMax Abort= 0
UNET Use Existing IB Tables= 0
UNET Froude Reduction=False
UNET Froude Limit= 0
UNET Froude Power= 0
UNET D1 Cores= 0
UNET WindReference=Eulerian
UNET WindDragFormulation=Hsu (1988)
UNET D2 Coriolis=0
UNET D2 Cores= 0
UNET D2 Theta= 1
UNET D2 Theta Warmup= 1
UNET D2 Z Tol= 0.01
UNET D2 Volume Tol= 0.01
UNET D2 Max Iterations= 20
UNET D2 Equation= 0
UNET D2 RampUpFraction=0.1
UNET D2 TimeSlices= 1
UNET D2 Turbulence Formulation=Non-Conservative (original)
UNET D2 Eddy Viscosity=0.3
UNET D2 Transverse Eddy Viscosity=0.1
UNET D2 Smagorinsky Mixing=0
UNET D2 BCVolumeCheck=0
UNET D2 Cores=0
UNET D2 SolverType=PARDISO (Direct)
UNET D2 Minimum Iterations= 2147483647
UNET D2 Maximum Iterations= 2147483647
UNET D2 Restart Number= 10
UNET D2 Relaxation Coeff=1.3
UNET D2 SOR Precondition Iterations= 10
UNET D2 ILUT Maximum Fill= 8
UNET D2 ILUT Tolerance=1E-08
UNET D1D2 MaxIter= 0
UNET D1D2 ZTol=0.01
UNET D1D2 QTol=0.1
UNET D1D2 MinQTol=1
Write IC File= 0
Write IC File at Fixed DateTime=0
Write IC File at Sim End=0
Echo Input=False
Echo Parameters=False
Echo Output=False
Write Detailed= 0
HDF Write Warmup=0
HDF Write Time Slices=0
HDF Flush=0
HDF Compression= 1
HDF Chunk Size= 1
HDF Spatial Parts= 1
HDF Use Max Rows=0
HDF Fixed Rows= 1
Calibration Method= 0
Calibration Iterations= 20
Calibration Max Change=0.05
Calibration Tolerance=0.2
Calibration Maximum=1.5
Calibration Minimum=0.5
Calibration Optimization Method= 1
WQ AD Non Conservative
WQ ULTIMATE=-1
WQ Max Comp Step=1HOUR
WQ Output Interval=15MIN
WQ Output Selected Increments= 0
WQ Output face flow=0
WQ Output face velocity=0
WQ Output face area=0
WQ Output face dispersion=0
WQ Output cell volume=0
WQ Output cell surface area=0
WQ Output cell continuity=0
WQ Output cumulative cell continuity=0
WQ Output face conc=0
WQ Output face dconc_dx=0
WQ Output face courant=0
WQ Output face peclet=0
WQ Output face adv mass=0
WQ Output face disp mass=0
WQ Output cell mass=0
WQ Output cell source sink temp=0
WQ Output nsm pathways=0
WQ Output nsm derived pathways=0
WQ Create Restart=0
WQ Fixed Restart=0
WQ System Summary=0
WQ Write To DSS=0
Sorting and Armoring Iterations= 10
XS Update Threshold= 0.02
Bed Roughness Predictor= 0
Hydraulics Update Threshold= 0.02
Energy Slope Method= 1
Volume Change Method= 1
Sediment Retention Method= 0
Sediment TS Multiplier= 1
Warm Up Method= 0
XS Weighting Method= 0
Number of US Weighted Cross Sections= 1
Number of DS Weighted Cross Sections= 1
Upstream XS Weight=0
Main XS Weight=1
Downstream XS Weight=0
Number of DS XS's Weighted with US Boundary= 1
Upstream Boundary Weight= 1
Weight of XSs Associated with US Boundary= 0
Number of US XS's Weighted with DS Boundary= 1
Downstream Boundary Weight= 0.5
Weight of XSs Associated with DS Boundary= 0.5
Percentile Method= 0
Sediment Output Level= 3
Mass or Volume Output= 0
Output Increment Type= 1
Profile and TS Output Increment= 1
Transport Output Increment 1
XS Output Flag= 0
XS Output Increment= 10
Read HDF5 Sediment Hotstart= 0
Sediment Hotstart Type= 0
Write Gradation File= 0
Read Gradation Hotstart= 0
Write HDF5 File= 1
Write Binary Output= 1
Write DSS Sediment File= 0
DSS Sediment Output Type= 1
SV Curve= 0
Specific Gage Flag= 0
Subcell Erosion Methods= 0
Subcell Deposition Methods= 0
Advection Scheme= 1
Matrix Solver= 0
Implicit Weighting Factor= 1
Maximum Outer Loop Convergence Iterations= 5
Convergence Maximum Absolute= 0.001
Convergence RMSE= 0.0001
Grain Fractions Max Abs Error= 0.001
Max Subgrid Regions= 1
Max Subgrid Length Scale= 3.402823E+38
Initial Layer Thickness= 3.402823E+38
Min Layer Thickness= 3.402823E+38
Max Layer Thickness= 3.402823E+38
Number of Layers= 5

--- GUMBR.f01 (steady flow) ---

Flow Title=Flow
Program Version=6.00
Number of Profiles= 6
Profile Names=01pct,10pct,04pct,02pct,0_2pct,01plus
River Rch & RM=GUMBR,Main            ,1161
     530     279     372     448     741     784
Boundary for River Rch & Prof#=GUMBR,Main            , 1
Up Type= 0
Dn Type= 3
Dn Slope=0.00962
Boundary for River Rch & Prof#=GUMBR,Main            , 2
Up Type= 0
Dn Type= 3
Dn Slope=0.00962
Boundary for River Rch & Prof#=GUMBR,Main            , 3
Up Type= 0
Dn Type= 3
Dn Slope=0.00962
Boundary for River Rch & Prof#=GUMBR,Main            , 4
Up Type= 0
Dn Type= 3
Dn Slope=0.00962
Boundary for River Rch & Prof#=GUMBR,Main            , 5
Up Type= 0
Dn Type= 3
Dn Slope=0.00962
Boundary for River Rch & Prof#=GUMBR,Main            , 6
Up Type= 0
Dn Type= 3
Dn Slope=0.00962
DSS Import GetInterval= 0
DSS Import GetPeak= 0
DSS Import FillOption= 0

--- GUMBR.g01 (geometry) ---

Geom Title=Geometry
Program Version=6.00

River Reach=GUMBR           ,Main
Reach XY= 30
2294552.07432748 495863.106193252294489.15704339495903.957765285
     2294447.173       495942.02      2294383.09      495988.864
     2294334.989      496028.862     2294324.243      496035.015
     2294290.237      496061.481     2294226.777      496100.974
     2294215.225      496102.998      2294179.56      496101.832
     2294147.306      496108.814     2294069.922      496160.853
      2294031.88      496170.552     2293982.116      496191.019
     2293926.392      496196.074     2293861.207      496215.804
     2293826.029      496217.011     2293788.749      496221.999
     2293761.109       496227.59     2293744.178      496234.215
     2293736.437      496240.644     2293734.276      496258.763
     2293728.701      496268.946     2293696.567       496289.42
     2293677.933      496306.488     2293655.441      496340.717
     2293633.474      496369.425     2293628.347        496372.6
     2293594.939      496378.415     2293530.217      496414.371

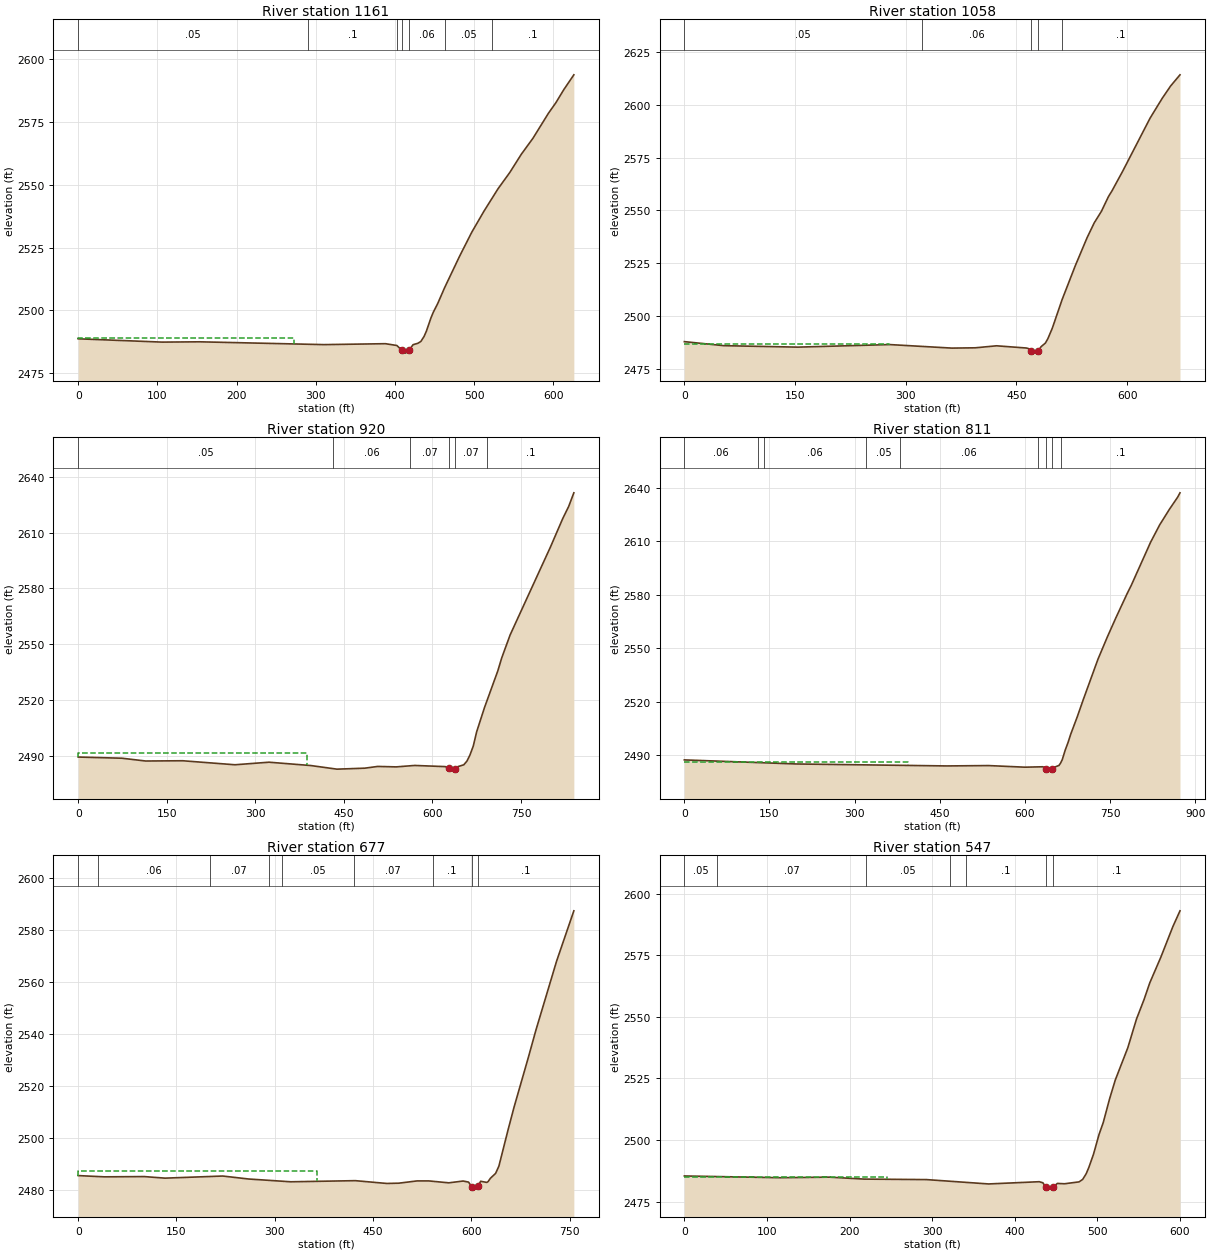
Type RM Length L Ch R = 1 ,1161    ,103.9,103.9,103.9
XS GIS Cut Line= 3
2294350.85477542495511.9509901542294447.95211022495798.786794728
2294633.20728315496063.452841788
#Sta/Elev= 30
       0 2488.61   106.1 2487.29   153.4 2487.41   310.4 2486.29     388 2486.66
   402.4 2485.94  408.282484.177   413.2  2482.9   416.7 2483.58  418.042484.188
   422.9 2486.26   428.8 2486.81   432.7 2487.54   436.8 2489.57   439.7 2491.66
   445.4  2496.9   448.3 2499.11   454.1 2502.74   462.7 2508.98   481.5 2521.45
   497.1 2531.15   512.5 2539.53   530.3 2548.48     545 2554.89   559.6 2562.19
   574.3 2568.56   593.8  2578.5   603.2 2582.71   613.3 2587.97   625.9 2593.83
#Mann= 7 ,-1,0
       0     .05       0     290      .1       0  402.82     .06       0
  408.28    .045       0  418.04     .06       0  462.82     .05       0
  522.82      .1       0
#XS Ineff= 2 , 0
          271.95  2489.1
Permanent Ineff=
       F       F
Bank Sta=408.28,418.04
XS Rating Curve= 0 ,0
Exp/Cntr(USF)=0,0
Exp/Cntr=0.3,0.1

Type RM Length L Ch R = 1 ,1058    ,139.3,138.3,137.2
XS GIS Cut Line= 3
2294334.94919518495515.6686931722294316.38662929495786.604503036
2294541.54208832496117.204616745
#Sta/Elev= 30
       0 2487.83    53.6 2485.92   153.9 2485.23   278.3 2486.44   362.5 2484.77
   394.2 2484.91     423 2485.86   463.4 2484.81   466.2 2484.55     4702483.493
   473.1  2482.5   474.8 2482.39   477.7 2482.59   479.32483.381   483.4 2485.44
   489.2 2487.15   492.5 2489.18   498.6 2494.21   511.8 2507.67   529.5  2523.6
   545.7 2537.05   555.4  2544.1   565.1 2549.54   574.7 2556.55   579.6 2559.34
   594.1 2568.66   631.1 2593.71   647.5 2603.07     659 2608.97   671.6 2614.21
#Mann= 5 ,-1,0
       0     .05       0  321.57     .06       0     470    .045       0
   479.3     .06       0  511.57      .1       0
#XS Ineff= 2 , 0
          276.84 2486.93
Permanent Ineff=
       F       F
Bank Sta=470,479.3
XS Rating Curve= 0 ,0
Exp/Cntr=0.3,0.1

Type RM Length L Ch R = 1 ,920     ,107.7,108.4,109.1
XS GIS Cut Line= 3
2293996.18934447495508.2053208772294068.32755431 495739.39923993
2294453.88288852 496195.52475611
#Sta/Elev= 30
       0  2489.3    74.2 2488.67   114.2 2487.17     177 2487.31   265.5 2485.15
   323.1 2486.53     394 2484.73   438.3 2482.79   485.4 2483.32   507.3 2484.25
   538.5 2484.01   569.8 2484.78   621.6 2484.16   628.2 2483.16   632.2 2481.73
   638.1 2482.85   642.6 2484.11     653 2485.13   658.3  2487.1   663.3 2490.28
   669.1 2495.24   674.8 2502.88   688.1 2515.94   710.7 2535.71   717.3 2542.67
   731.5 2554.99   799.7 2602.21   820.6 2617.58   830.6 2624.04   839.4 2631.41
#Mann= 6 ,-1,0
       0     .05       0  432.19     .06       0  562.19     .07       0
   628.2    .045       0   638.1     .07       0  692.19      .1       0
#XS Ineff= 2 , 0
          386.75 2491.33
Permanent Ineff=
       F       F
Bank Sta=628.2,638.1
XS Rating Curve= 0 ,0
Exp/Cntr(USF)=0,0
Exp/Cntr=0.3,0.1

Type RM Length L Ch R = 1 ,811     ,132.5,134.1,134.9
XS GIS Cut Line= 4
2293922.45967675495546.2413765272293949.89839711495694.305707665
2294160.68635925496001.9417450712294366.66103433496284.653048273
#Sta/Elev= 30
       0 2487.51   197.7 2485.23   462.2 2484.13   536.2 2484.33   599.9 2483.43
   631.4 2483.66   634.3 2483.32   637.12482.525     640 2481.48   642.8 2481.22
   648.32482.452   651.4 2483.35     660  2484.4   662.9 2485.72   665.8  2487.6
     671 2492.94     676 2497.23   680.9 2502.04   692.5 2511.86     703 2521.41
   728.7 2543.91   745.9 2556.89   760.2 2567.08   779.9 2580.56   787.6  2585.5
   821.5 2609.56   837.5 2619.29   854.7 2628.04   869.1 2634.78   873.3 2637.26
#Mann= 9 ,-1,0
       0     .06       0     130     .05       0     140     .06       0
  320.59     .05       0  380.59     .06       0  623.51     .07       0
   637.1    .045       0   648.3     .07       0  663.51      .1       0
#XS Ineff= 2 , 0
          394.12  2486.3
Permanent Ineff=
       F       F
Bank Sta=637.1,648.3
XS Rating Curve= 0 ,0
Exp/Cntr(USF)=0,0
Exp/Cntr=0.3,0.1

Type RM Length L Ch R = 1 ,677     ,129,130,131.1
XS GIS Cut Line= 3
2293845.30467659495601.3942962842293853.72752702495701.799541698
 2294184.3831486496267.956519311
#Sta/Elev= 30
       0 2485.55    39.9 2485.07   100.8 2485.17   132.5 2484.57   220.5 2485.38
     260 2484.24   324.3 2483.17   422.9  2483.6   470.8 2482.53   489.1 2482.63
   517.3 2483.51   534.9 2483.51   565.6 2482.77   587.5 2483.46   595.7 2483.05
   600.4 2481.35     605 2480.35   609.72481.362   614.2 2483.36   623.5 2482.93
   625.5 2483.23   629.1 2484.53     637  2486.4     642 2489.17   655.9 2503.01
   665.2 2511.88     687 2530.98   698.7 2541.59     730 2567.88   756.4 2587.26
#Mann= 9 ,-1,0
       0     .05       0      30     .06       0  200.76     .07       0
  290.76     .06       0  310.76     .05       0  420.76     .07       0
  540.76      .1       0   600.4    .045       0   609.7      .1       0
#XS Ineff= 2 , 0
          364.43 2487.18
Permanent Ineff=
       F       F
Bank Sta=600.4,609.7
XS Rating Curve= 0 ,0
Exp/Cntr(USF)=0,0
Exp/Cntr=0.3,0.1

Type RM Length L Ch R = 1 ,547     ,104.8,105.8,106.8
XS GIS Cut Line= 4
 2293837.5584082495774.0545057832293920.16327353496032.424660802
2294017.15047705496250.091083342 2294069.1646307496324.184135334
#Sta/Elev= 30
       0 2485.43   115.9 2484.72   175.5 2484.95   217.5 2484.16     293 2483.96
   368.4 2482.19   429.7  2483.1   434.1 2482.66   437.62480.957   438.4 2480.51
   442.9 2480.09   446.92481.069   451.6  2482.4   460.4 2482.27   477.9 2483.03
   482.3 2484.04   486.7 2486.45   489.9 2489.03   495.4 2494.27   502.1 2502.29
   507.2 2507.12   514.8 2516.66   521.8 2524.41   536.9 2537.44   547.5 2549.17
   556.6 2557.03   563.5 2563.78   576.9  2574.2   591.5 2586.64   600.1 2593.02
#Mann= 7 ,-1,0
       0     .05       0      40     .07       0     220     .05       0
  321.25     .07       0  341.25      .1       0   437.6    .045       0
   446.9      .1       0
#XS Ineff= 2 , 0
          244.94 2485.19
Permanent Ineff=
       F       F
Bank Sta=437.6,446.9
XS Rating Curve= 0 ,0
Exp/Cntr(USF)=0,0
Exp/Cntr=0.3,0.1

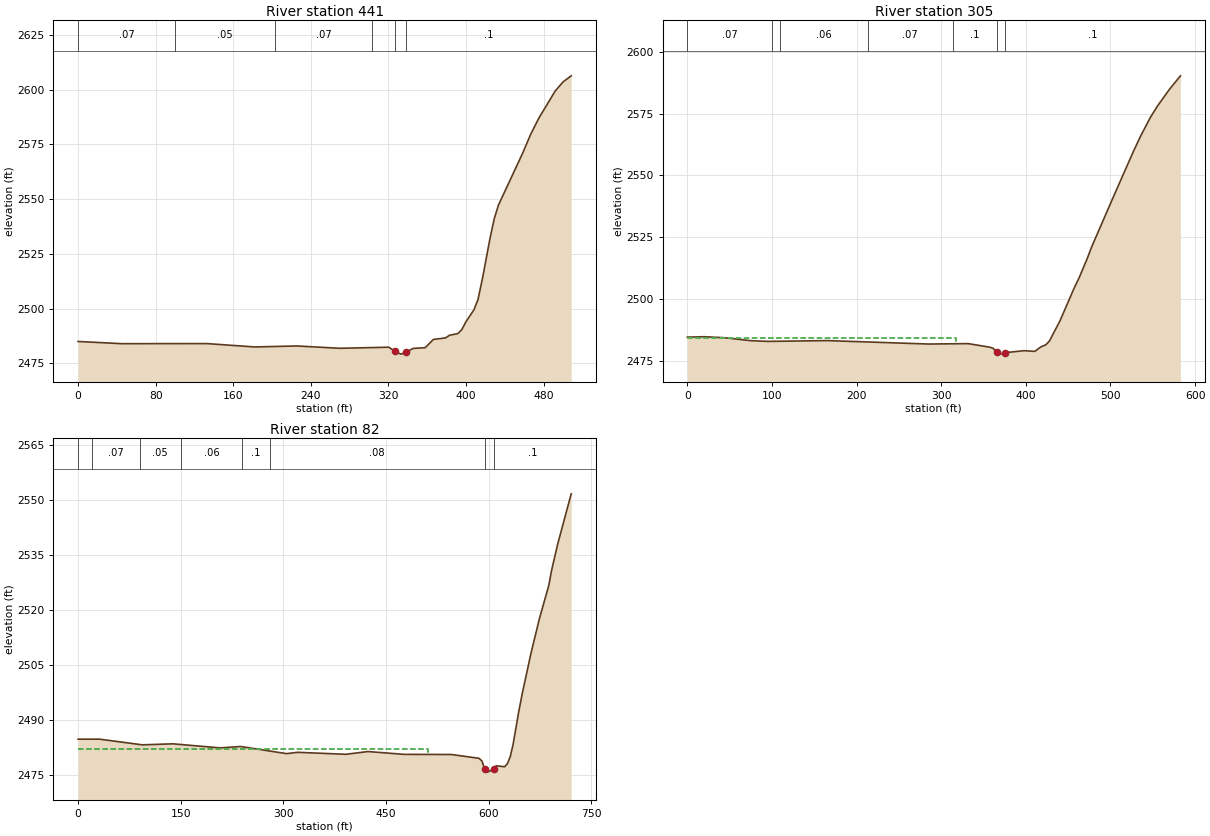
Type RM Length L Ch R = 1 ,441     ,135.4,135.8,135.9
XS GIS Cut Line= 3
2293832.34469459 495884.321245972293833.90033702496037.572417629
2293938.37390192496376.969758413
#Sta/Elev= 30
       0 2484.95    44.9 2483.95   132.9 2483.98   182.1 2482.45   225.2  2482.9
     270 2481.84   320.3 2482.33     327 2480.39   332.8 2479.17   338.32480.108
   345.4 2481.78   357.9 2482.12   366.3 2485.88   378.8 2486.58     383  2487.8
   391.6 2488.57   395.6 2490.34   399.8 2493.92   408.1  2499.4   412.3 2504.12
   417.2 2514.35   424.9 2532.54   429.1 2541.09   433.4 2547.27   458.4 2571.04
   466.7 2579.67   475.1 2587.04   491.9 2599.39   500.2 2603.64   508.4 2606.33
#Mann= 6 ,-1,0
       0     .07       0     100     .05       0  203.26     .07       0
  303.26      .1       0     327    .045       0   338.3      .1       0
Bank Sta=327,338.3
XS Rating Curve= 0 ,0
Exp/Cntr=0.3,0.1

Type RM Length L Ch R = 1 ,305     ,221.5,223.2,202.2
XS GIS Cut Line= 4
2293808.90471369495898.3268876472293703.17101499496060.356038896
2293779.37448612496318.9390802782293865.64256665 496401.88915771
#Sta/Elev= 30
       0 2484.49    19.9 2484.65    43.1 2484.27    74.8 2483.06    95.1 2482.76
   165.8 2483.08   285.1 2481.69   331.9 2481.86     357 2480.44   361.1 2480.01
   366.22478.333   369.5  2477.6   375.92478.195   397.9    2479   410.7 2478.71
   417.2 2480.41   423.7 2481.42   427.9 2482.91   440.4 2491.12     457 2504.26
   463.1 2508.62   472.1 2515.94   477.8 2521.05     503 2540.95   527.4 2559.96
   535.9 2566.13   547.2 2573.53   555.7  2578.2   569.6 2584.85   582.7 2590.38
#Mann= 7 ,-1,0
       0     .07       0     100     .05       0     110     .06       0
  213.48     .07       0  313.48      .1       0   366.2    .045       0
   375.9      .1       0
#XS Ineff= 2 , 0
          317.53 2483.97
Permanent Ineff=
       F       F
Bank Sta=366.2,375.9
XS Rating Curve= 0 ,0
Exp/Cntr(USF)=0,0
Exp/Cntr=0.3,0.1

Type RM Length L Ch R = 1 ,82      ,,,
XS GIS Cut Line= 5
2293804.25950934 495868.796660082293562.54785056 496146.21754471
2293594.52645871496347.5049109992293617.79315535496432.394527915
2293646.07094226496486.092007709
#Sta/Elev= 30
       0 2484.66    31.5 2484.66    93.9 2483.11   138.4 2483.39   207.4 2482.28
   237.6 2482.66   304.6 2480.71   320.7 2481.07   391.2 2480.53   423.6 2481.28
   476.3 2480.51   545.1 2480.48   585.9 2479.43   590.1 2478.69   594.12476.515
   598.4 2475.66   608.3 2476.64   610.8 2477.39   623.3 2477.13   627.4 2478.02
   631.6 2479.98   635.7 2483.33     644 2492.32   649.3 2497.41   662.1 2508.42
   674.2 2517.66   687.8 2526.67   691.7 2530.62   700.6 2537.82   720.5 2551.66
#Mann= 8 ,-1,0
       0     .05       0      20     .07       0      90     .05       0
     150     .06       0     240      .1       0     280     .08       0
   594.1    .045       0   608.3      .1       0
#XS Ineff= 2 , 0
          511.04 2481.93
Permanent Ineff=
       F       F
Bank Sta=594.1,608.3
XS Rating Curve= 0 ,0
Exp/Cntr(USF)=0,0
Exp/Cntr=0.3,0.1
LCMann Table=0

Chan Stop Cuts=-1
Use User Specified Reach Order=0
Composite Channel Slope=5